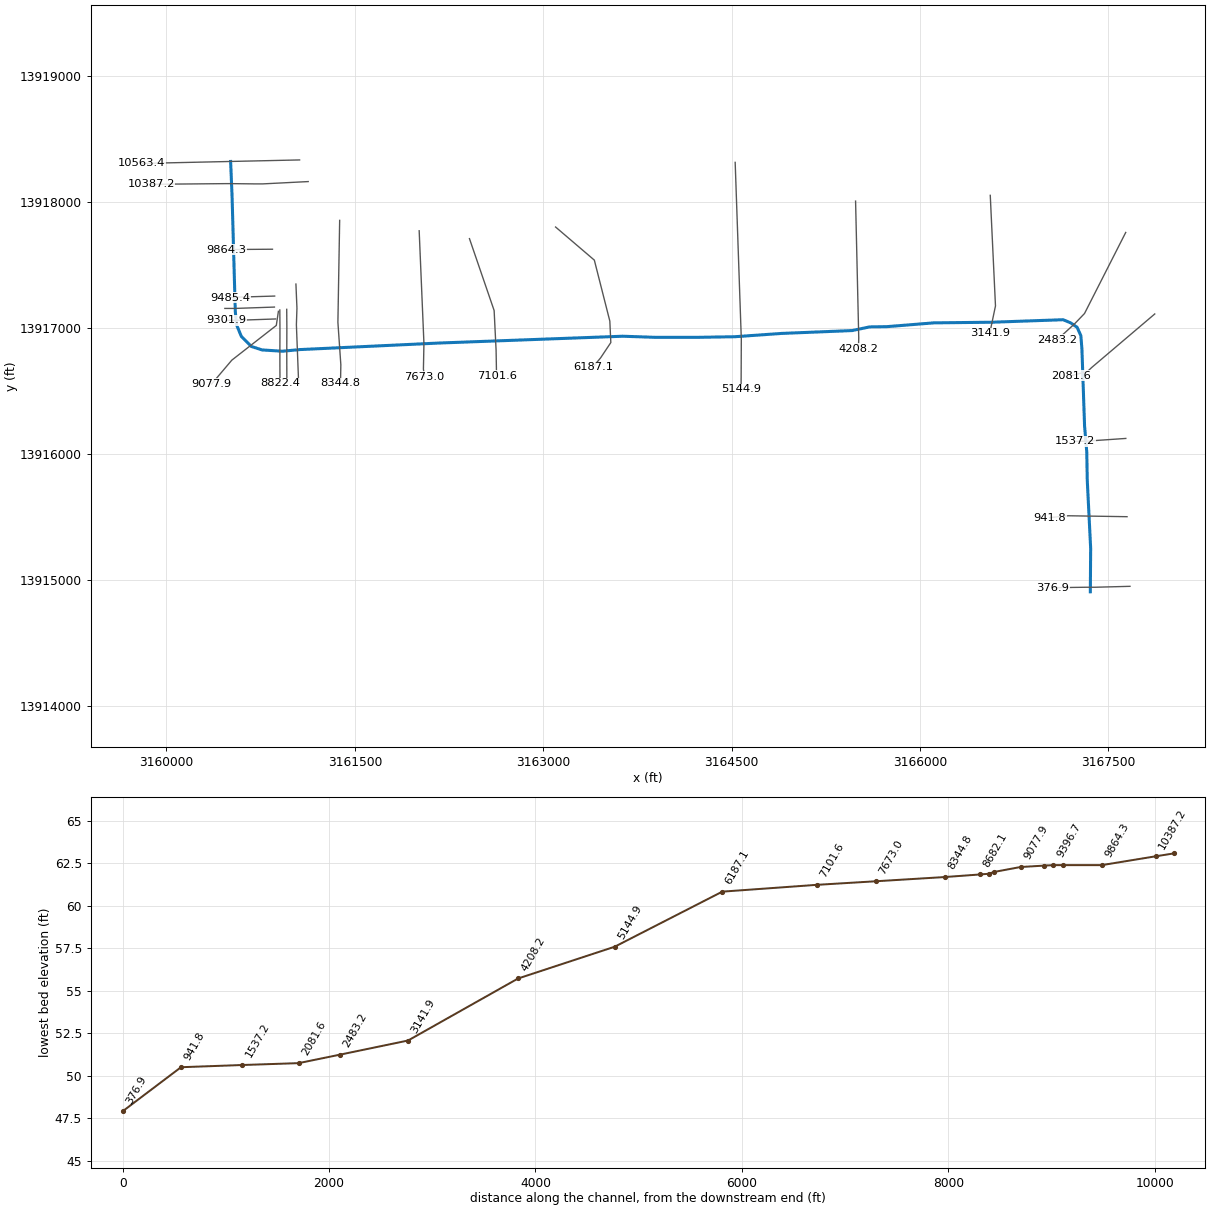
--- P130-02-02.PRJ (project) ---

Proj Title=P130-02-02
Current Plan=p02
Default Exp/Contr=.3,.1
English Units
Geom File=g01
Flow File=f01
Flow File=f02
Plan File=p01
Plan File=p02
Y Axis Title=Elevation
X Axis Title(PF)=Main Channel Distance
X Axis Title(XS)=Station
BEGIN DESCRIPTION:
Greens Bayou Watershed
Tributary 2.01 to Williams Gully
HCFCD Unit P130-02-02
Flood Hazard Model
10, 2, 1, 0.2% Event
Filename P130-02-02.prj
Prepared by:  Watershed Concepts  Date:
Reviewed by:                      Date:
STATUS FINAL
END DESCRIPTION:
DSS Export Rating Curves= 0
DSS Export Rating Curve Sorted= 0
DSS Export Volume Flow Curves= 0
DXF OffsetX= 0
DXF OffsetY= 0
DXF ScaleX= 1
DXF ScaleY= 10

--- P130-02-02.p02 (plan) ---

Plan Title=Floodway
Version=Version 3.0.1  Mar 2001
Short Identifier=Floodway0607
Geom File=g01
Flow File=f02
Subcritical Flow
K Sum by GR= 0
Std Step Tol= 0.01
Critical Tol= 0.01
Num of Std Step Trials= 20
Max Error Tol= 0.3
Flow Tol Ratio= 0.001
Split Flow NTrial= 30
Split Flow Tol= 0.02
Split Flow Ratio= 0.02
Log Output Level= 0
Friction Slope Method= 1
Unsteady Friction Slope Method= 2
Parabolic Critical Depth
Global Vel Dist= 0 , 0 , 0
Global Log Level= 0
CheckData=True
Encroach Param=-1 ,0,0, 2
Encroach River=P130-02-02
Encroach Reach=Reach - 1
Encroach Node=10563.4
       1  4915.9  5057.8
Encroach Node=10387.2
       1    4950    5036
Encroach Node=9864.3
       1    4950    5030
Encroach Node=9485.4
       1    4950    5025
Encroach Node=9396.7
       1  4964.5    5031
Encroach Node=9349.3
       1  4964.5    5031
Encroach Node=9301.9
       1  4964.5    5031
Encroach Node=9077.9
       1  4945.7  5085.7
Encroach Node=8822.4
       1  4964.5    5035
Encroach Node=8794.8
       1  4964.5    5035
Encroach Node=8767.2
       1  4964.5    5035
Encroach Node=8682.1
       1    4958  5043.5
Encroach Node=8344.8
       1    4958  5043.5
Encroach Node=7673.0
       1  4959.7  5039.3
Encroach Node=7101.6
       1  4959.7  5039.3
Encroach Node=6187.1
       1    4925    5055
Encroach Node=5144.9
       1    4955    5050
Encroach Node=4208.2
       1  4963.9  5022.2
Encroach Node=3141.9
       1  4956.1  5041.7
Encroach Node=2483.2
       1  4961.2  5031.8
Encroach Node=2081.6
       1  4961.2  5031.8
Encroach Node=1537.2
       1  4966.2  5033.4
Encroach Node=941.8
       1 4970.59 5029.06
Encroach Node=376.9
       1 4970.59 5029.06
Encroach Reach=P130-02-02_0004
Encroach Node=10563.4
       1  4915.9  5057.8
Encroach Node=10387.2
       1    4950    5036
Encroach Node=9864.3
       1    4950    5030
Encroach Node=9485.4
       1    4950    5025
Encroach Node=9396.7
       1  4964.5    5031
Encroach Node=9349.3
       1  4964.5    5031
Encroach Node=9301.9
       1  4964.5    5031
Encroach Node=9077.9
       1  4945.7  5085.7
Encroach Node=8822.4
       1  4964.5    5035
Encroach Node=8794.8
       1  4964.5    5035
Encroach Node=8767.2
       1  4964.5    5035
Encroach Node=8682.1
       1    4958  5043.5
Encroach Node=8344.8
       1    4958  5043.5
Encroach Node=7673.0
       1  4959.7  5039.3
Encroach Node=7101.6
       1  4959.7  5039.3
Encroach Node=6187.1
       1    4925    5055
Encroach Node=5144.9
       1    4955    5050
Encroach Node=4208.2
       1  4963.9  5022.2
Encroach Node=3141.9
       1  4956.1  5041.7
Encroach Node=2483.2
       1  4961.2  5031.8
Encroach Node=2081.6
       1  4961.2  5031.8
Encroach Node=1537.2
       1  4966.2  5033.4
Encroach Node=941.8
       1 4970.59 5029.06
Encroach Node=376.9
       1 4970.59 5029.06
Computation Interval=1HOUR
Output Interval=1HOUR
Run HTab= 0
Run UNet= 0
Run PostProcess= 0
UNET Theta= 1
UNET ZTol= 0.02
UNET ZSATol= 0.1
UNET MxIter= 20
UNET MaxInSteps= 20
UNET DtIC= 0
UNET DtMin= 0
UNET MaxCRTS= 20
UNET WFStab= 2
UNET SFStab= 1
UNET WFX= 1
UNET SFX= 1
UNET Convert EG Bridges=-1
UNET Use Existing IB Tables=-1
Instantaneous Interval=1HOUR
DSS File=dss
Write IC File= 0
Write Velocity= 0
Write Detailed= 0

--- P130-02-02.p01 (plan) ---

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Plan Title=FEMA Effective June 2007
Short Identifier=FEMAeff0607
Geom File=g01
Flow File=f01
Encroach Param=-1 ,0,0, 0

--- P130-02-02.f02 (steady flow) ---

Flow Title= Floodway
Number of Profiles= 2
Profile Names=1PCT_100yr, 1PCTFloodway_100yrFW
River Rch & RM=P130-02-02,P130-02-02_0004,10563.4
     167     167
River Rch & RM=P130-02-02,P130-02-02_0004,10387.2
     186     186
River Rch & RM=P130-02-02,P130-02-02_0004,9864.3
     201     201
River Rch & RM=P130-02-02,P130-02-02_0004,9485.4
     218     218
River Rch & RM=P130-02-02,P130-02-02_0004,9077.9
     236     236
River Rch & RM=P130-02-02,P130-02-02_0004,8682.1
     253     253
River Rch & RM=P130-02-02,P130-02-02_0004,8344.8
     290     290
River Rch & RM=P130-02-02,P130-02-02_0004,7673
     325     325
River Rch & RM=P130-02-02,P130-02-02_0004,7101.6
     391     391
River Rch & RM=P130-02-02,P130-02-02_0004,6187.1
     757     757
River Rch & RM=P130-02-02,P130-02-02_0004,5144.9
     845     845
River Rch & RM=P130-02-02,P130-02-02_0004,4208.2
     956     956
River Rch & RM=P130-02-02,P130-02-02_0004,3141.9
    1082    1082
River Rch & RM=P130-02-02,P130-02-02_0004,2081.6
    1153    1153
River Rch & RM=P130-02-02,P130-02-02_0004,1537.2
    1236    1236
River Rch & RM=P130-02-02,P130-02-02_0004,941.8
    1320    1320
Boundary for River Rch & Prof#=P130-02-02,P130-02-02_0004, 1
Up Type= 0
Dn Type= 3
Dn Slope= 0.00700
Boundary for River Rch & Prof#=P130-02-02,P130-02-02_0004, 2
Up Type= 0
Dn Type= 1
Dn Known WS=56.24

--- P130-02-02.f01 (steady flow) ---

Flow Title= FEMA Effective June 2007
Number of Profiles= 4
Profile Names=10PCT_10yr, 2PCT_50yr, 1PCT_100yr, 0.2PCT_500yr
River Rch & RM=P130-02-02,P130-02-02_0004,10563.4
      95     143     167     239
River Rch & RM=P130-02-02,P130-02-02_0004,10387.2
     105     159     186     266
River Rch & RM=P130-02-02,P130-02-02_0004,9864.3
     114     171     201     287
River Rch & RM=P130-02-02,P130-02-02_0004,9485.4
     123     186     218     312
River Rch & RM=P130-02-02,P130-02-02_0004,9077.9
     134     202     236     338
River Rch & RM=P130-02-02,P130-02-02_0004,8682.1
     143     216     253     362
River Rch & RM=P130-02-02,P130-02-02_0004,8344.8
     164     247     290     414
River Rch & RM=P130-02-02,P130-02-02_0004,7673
     184     277     325     465
River Rch & RM=P130-02-02,P130-02-02_0004,7101.6
     222     334     391     560
River Rch & RM=P130-02-02,P130-02-02_0004,6187.1
     429     646     757    1084
River Rch & RM=P130-02-02,P130-02-02_0004,5144.9
     478     721     845    1208
River Rch & RM=P130-02-02,P130-02-02_0004,4208.2
     542     816     956    1368
River Rch & RM=P130-02-02,P130-02-02_0004,3141.9
     613     923    1082    1548
River Rch & RM=P130-02-02,P130-02-02_0004,2081.6
     653     984    1153    1649
River Rch & RM=P130-02-02,P130-02-02_0004,1537.2
     700    1055    1236    1768
River Rch & RM=P130-02-02,P130-02-02_0004,941.8
     747    1126    1320    1888
Boundary for River Rch & Prof#=P130-02-02,P130-02-02_0004, 1
Up Type= 0
Dn Type= 3
Dn Slope= 0.00700
Boundary for River Rch & Prof#=P130-02-02,P130-02-02_0004, 2
Up Type= 0
Dn Type= 3
Dn Slope= 0.00700
Boundary for River Rch & Prof#=P130-02-02,P130-02-02_0004, 3
Up Type= 0
Dn Type= 3
Dn Slope= 0.00700
Boundary for River Rch & Prof#=P130-02-02,P130-02-02_0004, 4
Up Type= 0
Dn Type= 3
Dn Slope= 0.00700

--- P130-02-02.g01 (geometry) ---

Geom Title=P130-02-02 June 2007
Version=Version 3.0.1  Mar 2001

River Reach=P130-02-02      ,P130-02-02_0004
Reach XY= 30
      3160510.75     13918324.84       3160522.5       13918045.
        3160548.       13917135.      3160558.25       13917028.
        3160596.       13916937.      3160675.75       13916857.
       3160761.5       13916829.      3160923.25       13916819.
        3161063.       13916832.        3162172.       13916884.
        3163633.       13916938.      3163897.25       13916929.
      3164220.75       13916929.      3164526.75       13916934.
       3164894.5       13916960.      3165460.75       13916983.
      3165599.25       13917012.      3165737.75       13917014.
        3166110.       13917044.      3166568.75       13917049.
      3167140.75       13917069.        3167200.       13917044.
       3167251.5       13917009.      3167281.25       13916943.
        3167290.       13916836.        3167311.       13916227.
       3167328.5       13916019.       3167332.5       13915794.
       3167359.5       13915256.        3167357.       13914910.

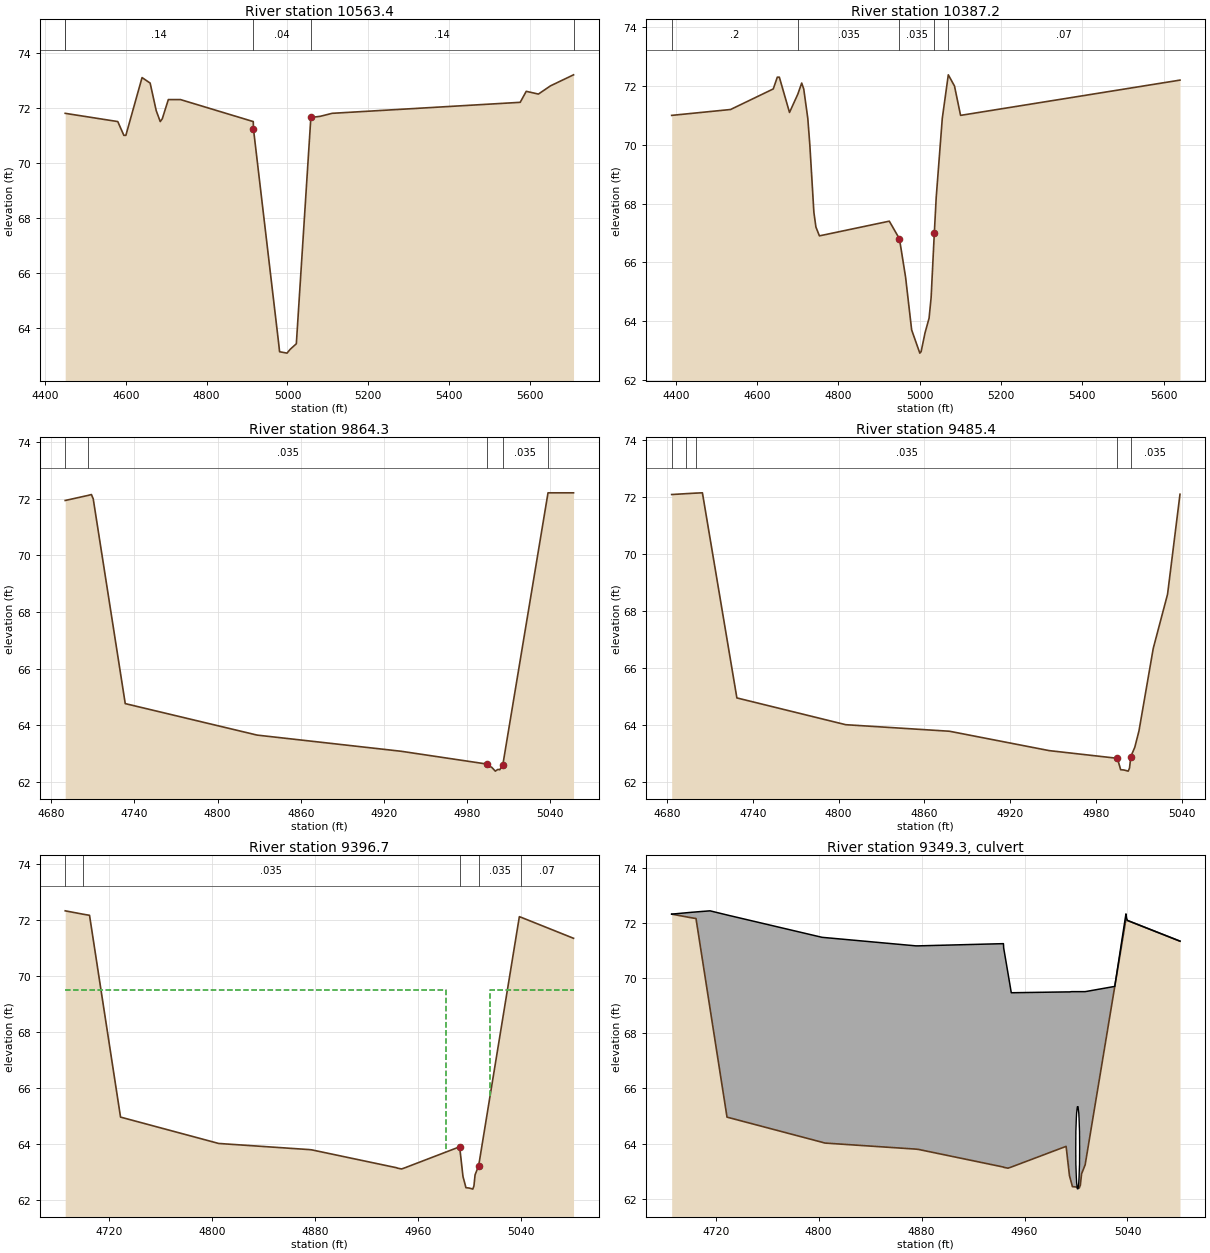
Type RM Length L Ch R = 1 ,10563.4 ,190.1,176.2,174.8
BEGIN DESCRIPTION:
Cross Section 10563.4
END DESCRIPTION:
XS GIS Cut Line= 2
      3161060.22     13918337.01      3159803.61     13918309.24
#Sta/Elev= 26
  4450.4    71.8  4580.4    71.5  4595.4      71  4600.4      71  4640.4    73.1
  4660.4    72.9  4675.4    71.9  4685.4    71.5  4690.4    71.6  4705.4    72.3
  4735.4    72.3  4915.4    71.5  4915.9   71.23  4978.1   63.45  4980.5   63.13
  4998.8   63.08  5006.8   63.22  5021.9   63.42  5057.8   71.65  5080.7   71.69
  5110.4    71.8  5575.4    72.2  5590.4    72.6  5620.4    72.5  5650.4    72.8
  5707.3    73.2
#Mann= 5 , 1 , 0
  4450.4      .2       0  4450.4     .14       0  4915.9     .04       0
  5057.8     .14       0  5707.3      .2       0
Bank Sta=4915.9,5057.8
XS Rating Curve= 0
Exp/Cntr=.3,.1

Type RM Length L Ch R = 1 ,10387.2 ,525,522.9,518.7
BEGIN DESCRIPTION:
Cross Section 10387.2-Interpolated
END DESCRIPTION:
XS GIS Cut Line= 6
      3161128.64     13918165.27      3160765.52     13918146.83
      3160708.55     13918146.83      3160510.63     13918149.01
       3160478.1     13918149.01      3159878.17     13918143.79
#Sta/Elev= 30
  4389.6      71  4534.6    71.2  4639.6    71.9  4649.6    72.3  4654.6    72.3
  4679.6    71.1    4700   71.72  4709.6    72.1  4714.6    71.9  4724.6    70.9
  4729.6      70  4739.6    67.7  4744.6    67.2  4753.2    66.9  4925.2    67.4
  4950.2    66.8  4965.2    65.5  4980.2    63.7  5000.3   62.91  5003.5   62.96
  5013.1    63.6  5023.1    64.1  5028.1    64.8    5036      67  5040.6    68.2
  5055.6    70.9  5070.4   72.38  5085.6      72  5100.6      71  5640.6    72.2
#Mann= 5 , 1 , 0
  4389.6      .2       0    4700    .035       0  4950.2    .035       0
    5036    .035       0  5070.4     .07       0
Bank Sta=4950.2,5036
XS Rating Curve= 0
Exp/Cntr=.3,.1

Type RM Length L Ch R = 1 ,9864.3  ,377.4,378.9,379.2
BEGIN DESCRIPTION:
Cross Section 9864.3
END DESCRIPTION:
XS GIS Cut Line= 2
      3160844.13     13917628.42      3160477.54      13917625.8
#Sta/Elev= 17
  4690.1   71.93  4706.7   72.11    4709   72.14  4710.3   71.99  4733.4   64.77
  4828.5   63.66  4932.4   63.09  4994.1   62.64  4996.4   62.55  4997.6   62.53
  5000.3   62.39  5002.1   62.45  5003.5   62.44  5005.7   62.61    5038   72.11
  5038.3    72.2  5056.7    72.2
#Mann= 5 , 1 , 0
  4690.1      .2       0  4706.7    .035       0  4994.1    .015       0
  5005.7    .035       0    5038     .07       0
Bank Sta=4994.1,5005.7
XS Rating Curve= 0
Exp/Cntr=.3,.1

Type RM Length L Ch R = 1 ,9485.4  ,86.9,88.7,88.9
BEGIN DESCRIPTION:
Cross Section 9485.4-Interpolated
END DESCRIPTION:
XS GIS Cut Line= 4
      3160861.51     13917256.69      3160578.45     13917248.43
      3160544.91     13917247.45      3160506.21     13917245.25
#Sta/Elev= 20
  4683.2    72.1  4693.2   72.13    4700   72.15  4704.7   72.16  4728.8   64.96
  4804.9   64.02  4877.5   63.79  4947.2   63.11  4994.9   62.84  4996.7   62.53
  4997.2   62.44  4999.5   62.43  5002.5   62.39  5003.4    62.5  5004.3    62.9
  5007.1   63.23    5010    63.8    5020    66.7    5030    68.6  5038.7   72.11
#Mann= 5 , 1 , 0
  4683.2      .2       0  4693.2     .07       0    4700    .035       0
  4994.9    .015       0  5004.3    .035       0
Bank Sta=4994.9,5004.3
XS Rating Curve= 0
Exp/Cntr=.5,.3

Type RM Length L Ch R = 1 ,9396.7  ,94.8,94.8,94.8
BEGIN DESCRIPTION:
Upstream Section of Bridge/Culvert/Weir
END DESCRIPTION:
XS GIS Cut Line= 3
      3160859.75     13917169.37      3160546.74     13917158.62
      3160464.94     13917158.62
#Sta/Elev= 29
  4685.8   72.32  4699.6    72.2  4704.7   72.16  4715.6    68.9  4728.8   64.96
  4802.6   64.05  4804.9   64.02  4875.6    63.8  4877.5   63.79  4943.6   63.15
  4943.8   63.14  4947.2   63.11  4949.7   63.15  4992.3    63.9  4994.9   62.84
  4996.7   62.53  4997.2   62.44  4999.5   62.43    5002    62.4  5002.5   62.39
  5003.4    62.5  5004.3    62.9  5007.1   63.23  5030.1   69.69  5038.7   72.11
  5038.8   72.11  5039.3    72.1    5040   72.09  5080.8   71.34
#Mann= 5 , 1 , 0
  4685.8     .07       0  4699.6    .035       0  4992.3    .015       0
  5007.1    .035       0    5040     .07       0
#XS Ineff= 2 , 0
       0    4982    69.5    5016       0    69.5
Permanent Ineff=
       F       F
Bank Sta=4992.3,5007.1
XS Rating Curve= 0
Exp/Cntr=.5,.3

Type RM Length L Ch R = 2 ,9349.3  ,,,
BEGIN DESCRIPTION:
DETENTION AREA U/S OF YGNACIO ROAD
Structure ID: P22-2
END DESCRIPTION:
Bridge Culvert--1,0,-1,-1, 0
Deck Dist Width WeirC Skew NumUp NumDn MinLoCord MaxHiCord MaxSubmerge Is_Ogee
10,74.8,3,0, 29, 29, , , .95, 0, 1,1,,
  4685.8  4699.6  4704.7  4715.6  4728.8  4802.6  4804.9  4875.6  4877.5  4943.6
  4943.8  4947.2  4949.7  4992.3  4994.9  4996.7  4997.2  4999.5    5002  5002.5
  5003.4  5004.3  5007.1  5030.1  5038.7  5038.8  5039.3    5040  5080.8
   72.32   72.38    72.4   72.44   72.29   71.48   71.47   71.17   71.17   71.25
   71.09   70.16   69.47    69.5    69.5   69.51   69.51   69.51   69.51   69.51
   69.51   69.51   69.51    69.7    72.3   72.33   72.17   72.09   71.34
   72.32    72.2   72.16    68.9   64.96   64.05   64.02    63.8   63.79   63.15
   63.14   63.11   63.15    63.9   62.84   62.53   62.44   62.43    62.4   62.39
    62.5    62.9   63.23   69.69   72.11   72.11    72.1   72.09   71.34
  4685.8  4699.6  4704.7  4715.6  4728.8  4802.6  4804.9  4875.6  4877.5  4943.6
  4943.8  4947.2  4949.7  4992.3  4994.9  4996.7  4997.2  4999.5    5002  5002.5
  5003.4  5004.3  5007.1  5030.1  5038.7  5038.8  5039.3    5040  5080.8
   72.32   72.38    72.4   72.44   72.29   71.48   71.47   71.17   71.17   71.25
   71.09   70.16   69.47    69.5    69.5   69.51   69.51   69.51   69.51   69.51
   69.51   69.51   69.51    69.7    72.3   72.33   72.17   72.09   71.34
   72.29   72.17   72.13   68.87   64.93   64.02   63.99   63.77   63.76   63.12
   63.11   63.08   63.12   63.87   62.81    62.5   62.41    62.4   62.37   62.36
   62.47   62.87    63.2   69.66   72.08   72.08   72.07   72.06   71.31
BR Coef= 1 , 0 , 0 ,1.25, 0 ,,,.8,-1,2,0,
WSPro=,,,, 1 ,,,, 0 ,,,, 0 ,,,,-1 ,-1 ,-1 , 0 , 0 , 0 , 0 , 0
Culvert=1,3,,74.8,.015,.2,1,1,3,62.35,5001.3,62.4,5001.3,Culvert #1  , 0 ,10
Culvert Bottom n=.015
BR U #Sta/Elev= 29
  4685.8   72.32  4699.6    72.2  4704.7   72.16  4715.6    68.9  4728.8   64.96
  4802.6   64.05  4804.9   64.02  4875.6    63.8  4877.5   63.79  4943.6   63.15
  4943.8   63.14  4947.2   63.11  4949.7   63.15  4992.3    63.9  4994.9   62.84
  4996.7   62.53  4997.2   62.44  4999.5   62.43    5002    62.4  5002.5   62.39
  5003.4    62.5  5004.3    62.9  5007.1   63.23  5030.1   69.69  5038.7   72.11
  5038.8   72.11  5039.3    72.1    5040   72.09  5080.8   71.34
BR U #Mann= 5
  4685.8     .07  4699.6    .035  4992.3    .015  5007.1    .035    5040     .07
BR U Banks=4992.3,5007.1
BR D #Sta/Elev= 29
  4685.8   72.29  4699.6   72.17  4704.7   72.13  4715.6   68.87  4728.8   64.93
  4802.6   64.02  4804.9   63.99  4875.6   63.77  4877.5   63.76  4943.6   63.12
  4943.8   63.11  4947.2   63.08  4949.7   63.12  4992.3   63.87  4994.9   62.81
  4996.7    62.5  4997.2   62.41  4999.5    62.4    5002   62.37  5002.5   62.36
  5003.4   62.47  5004.3   62.87  5007.1    63.2  5030.1   69.66  5038.7   72.08
  5038.8   72.08  5039.3   72.07    5040   72.06  5080.8   71.31
BR D #Mann= 5
  4685.8     .07  4699.6    .035  4992.3    .015  5007.1    .035    5040     .07
BR D Banks=4992.3,5007.1
BC Design=,, 0 ,, 0 ,,,,,,

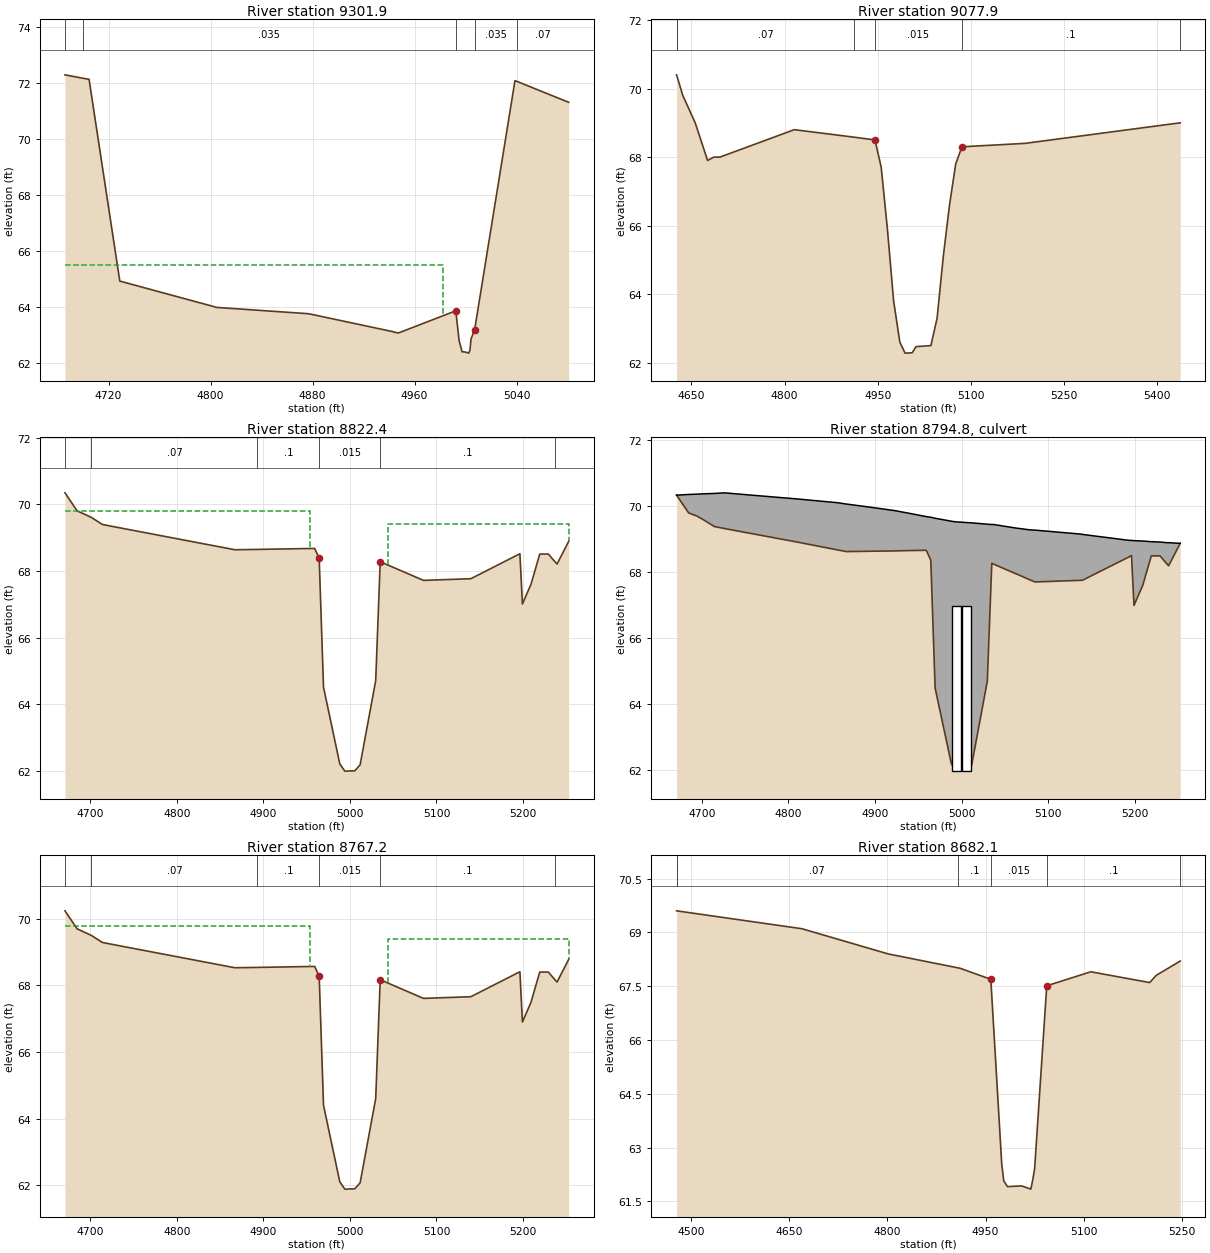
Type RM Length L Ch R = 1 ,9301.9  ,224,224,224
BEGIN DESCRIPTION:
Downstream Section of Bridge/Culvert/Weir
END DESCRIPTION:
XS GIS Cut Line= 3
      3160868.79       13917075.      3160555.78     13917064.26
      3160473.98     13917064.26
#Sta/Elev= 29
  4685.8   72.29  4699.6   72.17  4704.7   72.13  4715.6   68.87  4728.8   64.93
  4802.6   64.02  4804.9   63.99  4875.6   63.77  4877.5   63.76  4943.6   63.12
  4943.8   63.11  4947.2   63.08  4949.7   63.12  4992.3   63.87  4994.9   62.81
  4996.7    62.5  4997.2   62.41  4999.5    62.4    5002   62.37  5002.5   62.36
  5003.4   62.47  5004.3   62.87  5007.1    63.2  5030.1   69.66  5038.7   72.08
  5038.8   72.08  5039.3   72.07    5040   72.06  5080.8   71.31
#Mann= 5 , 1 , 0
  4685.8     .07       0  4699.6    .035       0  4992.3    .015       0
  5007.1    .035       0    5040     .07       0
#XS Ineff= 2 , 0
       0    4982    65.5    5016       0    65.5
Permanent Ineff=
       F       F
Bank Sta=4992.3,5007.1
XS Rating Curve= 0
Exp/Cntr=.5,.3

Type RM Length L Ch R = 1 ,9077.9  ,201.2,255.5,301.1
BEGIN DESCRIPTION:
Cross Section 9077.9-Interpolated
END DESCRIPTION:
XS GIS Cut Line= 4
      3160891.42     13917135.85      3160874.52     13917023.51
      3160520.29     13916748.09       3160359.2     13916558.37
#Sta/Elev= 25
  4626.1    70.4  4636.1    69.8  4656.1      69  4676.1    67.9  4686.1      68
  4696.1      68  4815.7    68.8  4912.3   68.58  4945.7    68.5  4955.7    67.7
  4965.7    65.9  4975.7    63.8  4985.7    62.6  4988.3    62.5  4994.1   62.28
  5005.6   62.29  5011.8   62.47  5035.7    62.5  5045.7    63.3  5055.7    65.1
  5065.7    66.6  5075.7    67.8  5085.7    68.3  5187.2    68.4  5437.3      69
#Mann= 6 , 1 , 0
  4626.1      .2       0  4626.1     .07       0  4912.3      .1       0
  4945.7    .015       0  5085.7      .1       0  5437.3      .2       0
#XS Ineff= 2 , 0
       0  4815.7    68.8               0
Permanent Ineff=
       F       F
Bank Sta=4945.7,5085.7
XS Rating Curve= 0
Exp/Cntr=.5,.3

Type RM Length L Ch R = 1 ,8822.4  ,55.2,55.2,55.2
BEGIN DESCRIPTION:
Upstream Section of Bridge/Culvert/Weir
END DESCRIPTION:
XS GIS Cut Line= 4
      3160902.53     13917146.32      3160903.75     13917002.39
        3160903.      13916778.7      3160903.75     13916564.43
#Sta/Elev= 26
  4670.8   70.35  4684.8   69.81  4701.4   69.61    4714    69.4  4725.8   69.34
  4867.1   68.64  4893.2   68.65  4959.3   68.68  4964.5   68.38  4969.5   64.51
  4988.3   62.21  4994.1   61.99  5005.6      62  5011.8   62.18  5029.8   64.71
    5035   68.28    5085   67.72  5139.7   67.77  5196.4   68.52  5199.3   67.01
  5209.3   67.61  5219.3   68.51  5229.3   68.51  5236.9   68.28  5239.3   68.21
  5252.7   68.89
#Mann= 6 , 1 , 0
  4670.8      .2       0  4701.4     .07       0  4893.2      .1       0
  4964.5    .015       0    5035      .1       0  5236.9      .2       0
#XS Ineff= 2 , 0
       0    4954   69.79    5044       0    69.4
Permanent Ineff=
       F       F
Bank Sta=4964.5,5035
XS Rating Curve= 0
Exp/Cntr=.5,.3

Type RM Length L Ch R = 2 ,8794.8  ,,,
BEGIN DESCRIPTION:
YGNACIO ROAD
Structure ID: P22-1
END DESCRIPTION:
Bridge Culvert--1,0,-1,-1, 0
Deck Dist Width WeirC Skew NumUp NumDn MinLoCord MaxHiCord MaxSubmerge Is_Ogee
10,35.2,3,0, 43, 43, , , .95, 0, 1,1,,
  4670.8  4684.8  4694.8  4701.4  4713.8    4714  4725.8  4789.3  4807.9  4856.9
  4867.1  4893.2  4923.1 4937.39  4937.5 4937.61  4959.3  4964.5  4969.5  4988.3
  4990.7  4994.1  5005.6  5011.8  5029.8    5035  5037.1 5063.59  5063.7 5063.81
  5078.5    5085  5137.8  5139.7  5193.7  5196.4  5199.3  5209.3  5219.3  5229.3
  5236.9  5239.3  5252.7
   70.34   70.36   70.37   70.38   70.39   70.39   70.41   70.27   70.23   70.11
   70.07   69.98   69.87    69.8    69.8    69.8   69.69   69.67   69.64   69.55
   69.54   69.53   69.51    69.5   69.46   69.45   69.45   69.34   69.34   69.34
   69.29   69.28   69.16   69.15   68.97   68.97   68.96   68.95   68.93   68.92
    68.9    68.9   68.88
   70.34    69.8    69.7    69.6    69.4   69.39   69.33   69.02   68.93   68.68
   68.63   68.64   68.65   68.66   68.66   68.66   68.67   68.37    64.5    62.2
   62.11   61.98   61.99   62.17    64.7   68.27   68.25   67.95   67.95   67.95
   67.78   67.71   67.76   67.76   68.47   68.51      67    67.6    68.5    68.5
   68.27    68.2   68.88
  4670.8  4684.8  4694.8  4701.4  4713.8    4714  4725.8  4789.3  4807.9  4856.9
  4867.1  4893.2  4923.1 4937.39  4937.5 4937.61  4959.3  4964.5  4969.5  4988.3
  4990.7  4994.1  5005.6  5011.8  5029.8    5035  5037.1 5063.59  5063.7 5063.81
  5078.5    5085  5137.8  5139.7  5193.7  5196.4  5199.3  5209.3  5219.3  5229.3
  5236.9  5239.3  5252.7
   70.34   70.36   70.37   70.38   70.39   70.39   70.41   70.27   70.23   70.11
   70.07   69.98   69.87    69.8    69.8    69.8   69.69   69.67   69.64   69.55
   69.54   69.53   69.51    69.5   69.46   69.45   69.45   69.34   69.34   69.34
   69.29   69.28   69.16   69.15   68.97   68.97   68.96   68.95   68.93   68.92
    68.9    68.9   68.88
   70.24    69.7    69.6    69.5    69.3   69.29   69.23   68.92   68.83   68.58
   68.53   68.54   68.55   68.56   68.56   68.56   68.57   68.27    64.4    62.1
   62.01   61.88   61.89   62.07    64.6   68.17   68.15   67.85   67.85   67.85
   67.68   67.61   67.66   67.66   68.37   68.41    66.9    67.5    68.4    68.4
   68.17    68.1   68.78
BR Coef= 1 , 0 , 0 ,1.25, 0 ,,,.8,-1,2,0,
WSPro=,,,, 1 ,,,, 0 ,,,, 0 ,,,,-1 ,-1 ,-1 , 0 , 0 , 0 , 0 , 0
Culvert=2,5,10,35.2,.015,.4,1,8,1,61.99,4994.1,61.89,4994.1,Culvert #1  , 0 ,10
Culvert Bottom n=.015
Culvert=2,5,10,35.2,.015,.4,1,8,1,61.99,5005.7,61.89,5005.7,Culvert #2  , 0 ,10
Culvert Bottom n=.015
BR U #Sta/Elev= 43
  4670.8   70.34  4684.8    69.8  4694.8    69.7  4701.4    69.6  4713.8    69.4
    4714   69.39  4725.8   69.33  4789.3   69.02  4807.9   68.93  4856.9   68.68
  4867.1   68.63  4893.2   68.64  4923.1   68.65 4937.39   68.66  4937.5   68.66
 4937.61   68.66  4959.3   68.67  4964.5   68.37  4969.5    64.5  4988.3    62.2
  4990.7   62.11  4994.1   61.98  5005.6   61.99  5011.8   62.17  5029.8    64.7
    5035   68.27  5037.1   68.25 5063.59   67.95  5063.7   67.95 5063.81   67.95
  5078.5   67.78    5085   67.71  5137.8   67.76  5139.7   67.76  5193.7   68.47
  5196.4   68.51  5199.3      67  5209.3    67.6  5219.3    68.5  5229.3    68.5
  5236.9   68.27  5239.3    68.2  5252.7   68.88
BR U #Mann= 6
  4670.8      .2  4701.4     .07  4893.2      .1  4964.5    .015    5035      .1
  5236.9      .2
BR U Banks=4964.5,5035
BR D #Sta/Elev= 43
  4670.8   70.24  4684.8    69.7  4694.8    69.6  4701.4    69.5  4713.8    69.3
    4714   69.29  4725.8   69.23  4789.3   68.92  4807.9   68.83  4856.9   68.58
  4867.1   68.53  4893.2   68.54  4923.1   68.55 4937.39   68.56  4937.5   68.56
 4937.61   68.56  4959.3   68.57  4964.5   68.27  4969.5    64.4  4988.3    62.1
  4990.7   62.01  4994.1   61.88  5005.6   61.89  5011.8   62.07  5029.8    64.6
    5035   68.17  5037.1   68.15 5063.59   67.85  5063.7   67.85 5063.81   67.85
  5078.5   67.68    5085   67.61  5137.8   67.66  5139.7   67.66  5193.7   68.37
  5196.4   68.41  5199.3    66.9  5209.3    67.5  5219.3    68.4  5229.3    68.4
  5236.9   68.17  5239.3    68.1  5252.7   68.78
BR D #Mann= 6
  4670.8      .2  4701.4     .07  4893.2      .1  4964.5    .015    5035      .1
  5236.9      .2
BR D Banks=4964.5,5035
BC Design=,, 0 ,, 0 ,,,,,,

Type RM Length L Ch R = 1 ,8767.2  ,85.1,85.1,85.1
BEGIN DESCRIPTION:
Downstream Section of Bridge/Culvert/Weir
END DESCRIPTION:
XS GIS Cut Line= 4
      3160957.49     13917151.43      3160958.71     13917007.51
      3160957.96     13916783.82      3160958.72     13916569.54
#Sta/Elev= 26
  4670.8   70.24  4684.8    69.7  4701.4    69.5    4714   69.29  4725.8   69.23
  4867.1   68.53  4893.2   68.54  4959.3   68.57  4964.5   68.27  4969.5    64.4
  4988.3    62.1  4994.1   61.88  5005.6   61.89  5011.8   62.07  5029.8    64.6
    5035   68.17    5085   67.61  5139.7   67.66  5196.4   68.41  5199.3    66.9
  5209.3    67.5  5219.3    68.4  5229.3    68.4  5236.9   68.17  5239.3    68.1
  5252.7   68.78
#Mann= 6 , 1 , 0
  4670.8      .2       0  4701.4     .07       0  4893.2      .1       0
  4964.5    .015       0    5035      .1       0  5236.9      .2       0
#XS Ineff= 2 , 0
       0    4954   69.79    5044       0    69.4
Permanent Ineff=
       F       F
Bank Sta=4964.5,5035
XS Rating Curve= 0
Exp/Cntr=.5,.3

Type RM Length L Ch R = 1 ,8682.1  ,335.7,337.3,339
BEGIN DESCRIPTION:
Cross Section 8682.1-Interpolated
END DESCRIPTION:
XS GIS Cut Line= 4
      3161030.86     13917351.99      3161038.95     13917160.31
      3161034.55      13917029.1      3161051.82     13916582.72
#Sta/Elev= 18
  4477.7    69.6  4669.5    69.1  4800.8    68.4  4907.7   68.01  4910.8      68
    4958   67.69  4974.7   62.54  4977.8   62.07  4983.5   61.91  5005.1   61.93
  5019.2   61.84  5022.2   62.11    5025   62.42  5043.5   67.51  5110.8    67.9
  5200.8    67.6  5210.8    67.8  5247.5    68.2
#Mann= 6 , 1 , 0
  4477.7      .2       0  4477.7     .07       0  4907.7      .1       0
    4958    .015       0  5043.5      .1       0  5247.5      .2       0
Bank Sta=4958,5043.5
XS Rating Curve= 0
Exp/Cntr=.3,.1

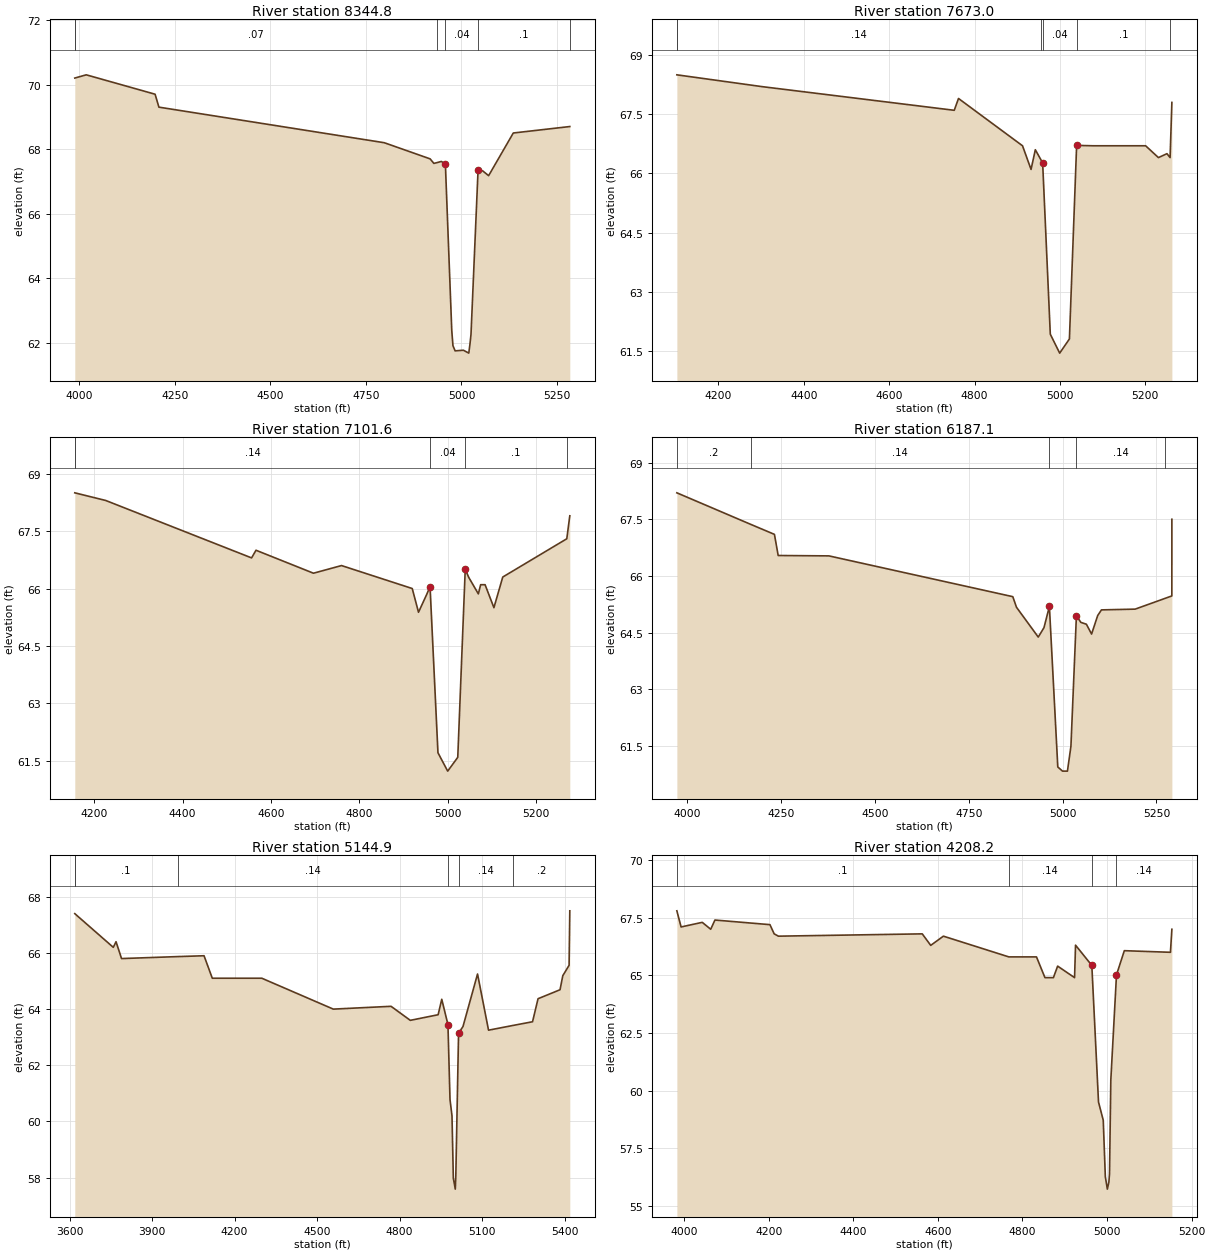
Type RM Length L Ch R = 1 ,8344.8  ,674,671.8,667.9
BEGIN DESCRIPTION:
Cross Section 8344.8
END DESCRIPTION:
XS GIS Cut Line= 4
      3161379.14     13917857.46      3161365.11     13917048.32
       3161388.5     13916711.57      3161385.89     13916563.81
#Sta/Elev= 22
  3988.8    70.2  4018.8    70.3  4198.8    69.7  4208.8    69.3  4798.1    68.2
  4918.1    67.7  4927.9   67.56  4934.9   67.58  4947.5   67.62    4958   67.54
  4974.7   62.39  4977.8   61.92  4983.5   61.76  5005.1   61.78  5019.2   61.69
  5022.2   61.96    5025   62.27  5043.5   67.36  5055.4   67.33  5071.1   67.18
  5135.6    68.5  5283.4    68.7
#Mann= 6 , 1 , 0
  3988.8      .2       0  3988.8     .07       0  4934.9      .1       0
    4958     .04       0  5043.5      .1       0  5283.4      .2       0
Bank Sta=4958,5043.5
XS Rating Curve= 0
Exp/Cntr=.3,.1

Type RM Length L Ch R = 1 ,7673.0  ,568.9,571.4,582.9
BEGIN DESCRIPTION:
Cross Section 7673.0-Interpolated
END DESCRIPTION:
XS GIS Cut Line= 4
      3162012.29     13917774.95      3162050.24     13916880.46
      3162046.09      13916677.3      3162054.61     13916616.42
#Sta/Elev= 19
  4102.5    68.5  4302.5    68.2  4752.5    67.6  4762.5    67.9  4912.5    66.7
  4932.5    66.1  4942.5    66.6  4956.9   66.32  4959.7   66.26  4977.6   61.92
  4999.6   61.44  5022.4    61.8  5039.3   66.71  5077.8    66.7    5201    66.7
    5231    66.4    5251    66.5  5258.3    66.4  5262.5    67.8
#Mann= 6 , 1 , 0
  4102.5      .2       0  4102.5     .14       0  4956.9      .1       0
  4959.7     .04       0  5039.3      .1       0  5258.3      .2       0
#XS Ineff= 2 , 0
       0  4942.5    66.6    5201       0    66.7
Permanent Ineff=
       F       F
Bank Sta=4959.7,5039.3
XS Rating Curve= 0
Exp/Cntr=.3,.1

Type RM Length L Ch R = 1 ,7101.6  ,903,914.5,915.2
BEGIN DESCRIPTION:
Cross Section 7101.6
END DESCRIPTION:
XS GIS Cut Line= 4
      3162412.79     13917712.47      3162609.23     13917141.86
      3162624.84     13916827.44      3162628.39     13916625.75
#Sta/Elev= 23
  4155.9    68.5  4225.9    68.3  4555.9    66.8  4565.9      67  4695.9    66.4
  4759.4    66.6  4919.4      66  4933.6   65.38  4951.9   65.84  4959.7   66.05
  4977.6   61.71  4999.6   61.23  5022.4   61.59  5039.3    66.5  5047.3   66.29
    5069   65.86  5074.2    66.1  5084.2    66.1  5104.2    65.5  5124.2    66.3
  5269.1    67.3  5269.2   67.31  5275.9    67.9
#Mann= 5 , 1 , 0
  4155.9      .2       0  4155.9     .14       0  4959.7     .04       0
  5039.3      .1       0  5269.2      .2       0
Bank Sta=4959.7,5039.3
XS Rating Curve= 0
Exp/Cntr=.3,.1

Type RM Length L Ch R = 1 ,6187.1  ,1010.3,1042.2,1041.5
BEGIN DESCRIPTION:
Cross Section 6187.1
END DESCRIPTION:
XS GIS Cut Line= 6
      3163098.59     13917804.65      3163407.14     13917541.97
      3163530.62     13917057.67      3163538.47     13916887.78
      3163457.17     13916766.45      3163394.63      13916691.4
#Sta/Elev= 24
    3972    68.2    4170   67.36    4232    67.1    4242   66.54  4377.2   66.53
  4867.2   65.45    4877   65.17    4935   64.38  4950.3   64.63  4964.7   65.19
  4987.1   60.94  4999.7   60.83  5012.8   60.83  5022.1   61.49  5036.7   64.95
  5048.4   64.77  5063.3   64.72  5077.1   64.46  5093.4   64.95  5103.4    65.1
  5193.3   65.12  5271.6    65.4    5291   65.47  5291.1    67.5
#Mann= 5 , 1 , 0
    3972      .2       0    4170     .14       0  4964.7     .04       0
  5036.7     .14       0  5271.6      .2       0
Bank Sta=4964.7,5036.7
XS Rating Curve= 0
Exp/Cntr=.3,.1

Type RM Length L Ch R = 1 ,5144.9  ,1016.2,936.7,934.5
BEGIN DESCRIPTION:
Cross Section 5144.9
END DESCRIPTION:
XS GIS Cut Line= 4
      3164528.72     13918317.71      3164573.62     13917028.67
      3164577.63     13916914.07      3164575.74     13916518.56
#Sta/Elev= 30
    3619    67.4    3759    66.2    3769    66.4    3789    65.8  3992.6   65.87
    4089    65.9    4119    65.1    4299    65.1    4559      64    4769    64.1
    4839    63.6  4940.2    63.8  4953.4   64.35  4975.9   63.45  4983.4   60.78
  4990.6    60.2  4995.5   57.98  5002.6   57.59  5004.5   58.06  5014.5   63.14
  5030.6   63.38  5083.5   65.25  5123.5   63.25  5213.3   63.42  5283.5   63.55
  5303.5   64.37  5383.5   64.69  5393.5   65.19  5416.4   65.56    5419    67.5
#Mann= 6 , 1 , 0
    3619      .2       0    3619      .1       0  3992.6     .14       0
  4975.9    .045       0  5014.5     .14       0  5213.3      .2       0
Bank Sta=4975.9,5014.5
XS Rating Curve= 0
Exp/Cntr=.3,.1

Type RM Length L Ch R = 1 ,4208.2  ,1076.1,1066.3,1053.7
BEGIN DESCRIPTION:
Cross Section 4208.2
END DESCRIPTION:
XS GIS Cut Line= 3
      3165487.53     13918010.18      3165512.79     13916923.91
      3165510.46     13916840.51
#Sta/Elev= 30
  3983.1    67.8  3993.1    67.1  4043.1    67.3  4063.1      67  4073.1    67.4
  4203.1    67.2  4213.1    66.8  4223.1    66.7  4563.1    66.8  4583.1    66.3
  4613.1    66.7  4767.8    65.8  4833.1    65.8  4853.1    64.9  4873.1    64.9
  4883.1    65.4  4923.1    64.9  4925.4   66.31  4963.9   65.43  4979.7    59.5
  4990.9   58.71  4995.8   56.26  5000.6   55.72  5004.2   56.02  5005.7   56.39
  5008.8   60.46  5022.2   65.02  5040.7   66.07  5149.7      66  5153.1      67
#Mann= 4 , 1 , 0
  3983.1      .1       0  4767.8     .14       0  4963.9     .04       0
  5022.2     .14       0
#XS Ineff= 2 , 0
       0  4925.4   66.31               0
Permanent Ineff=
       F       F
Bank Sta=4963.9,5022.2
XS Rating Curve= 0
Exp/Cntr=.3,.1

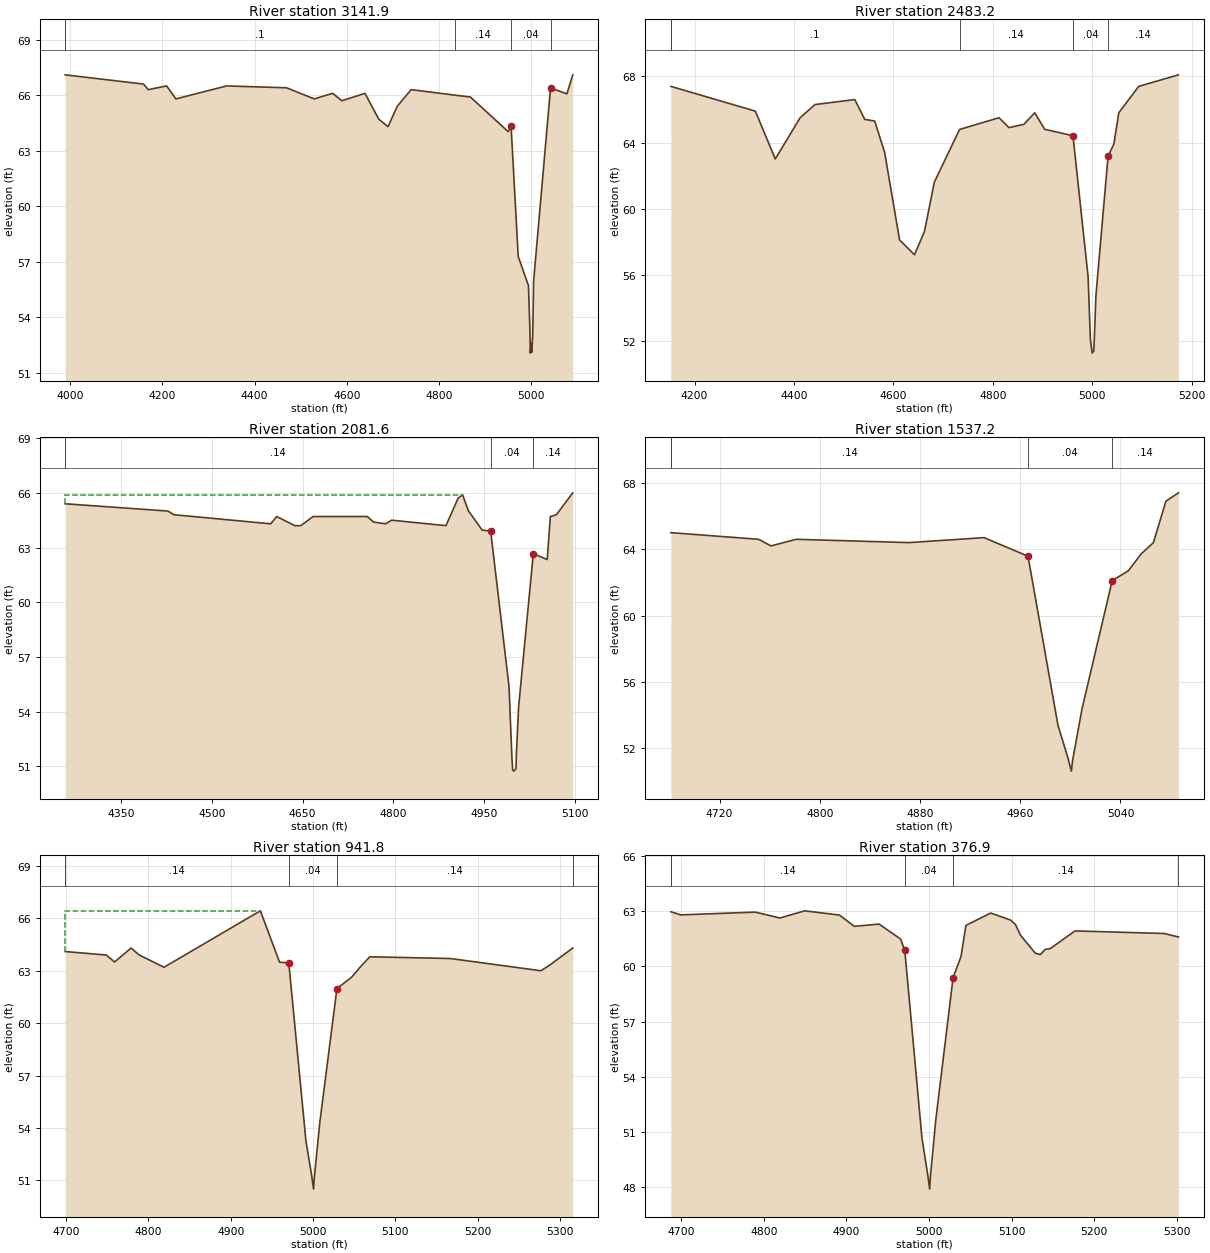
Type RM Length L Ch R = 1 ,3141.9  ,689.9,658.7,620.3
BEGIN DESCRIPTION:
Cross Section 3141.9
END DESCRIPTION:
XS GIS Cut Line= 4
      3166560.03      13918056.1      3166601.62     13917178.34
      3166566.11     13917010.22      3166561.79     13916960.34
#Sta/Elev= 30
  3989.3    67.1  4159.3    66.6  4169.3    66.3  4209.3    66.5  4229.3    65.8
  4339.3    66.5  4469.3    66.4  4529.3    65.8  4569.3    66.1  4589.3    65.7
  4639.3    66.1  4669.3    64.7  4689.3    64.3  4709.3    65.4  4739.3    66.3
  4834.9      66    4868    65.9  4949.9   64.03  4956.1   64.33  4971.6   57.29
  4993.8   55.72  4996.9   53.35  4997.8   52.07  4999.9    52.6  5001.2   52.12
  5003.1   53.07    5005   55.97  5041.7    66.4  5077.1   66.07  5089.9    67.1
#Mann= 5 , 1 , 0
  3989.3      .2       0  3989.3      .1       0  4834.9     .14       0
  4956.1     .04       0  5041.7     .14       0
#XS Ineff= 2 , 0
       0  4739.3    66.3               0
Permanent Ineff=
       F       F
Bank Sta=4956.1,5041.7
XS Rating Curve= 0
Exp/Cntr=.3,.1

Type RM Length L Ch R = 1 ,2483.2  ,431.9,401.6,372.9
BEGIN DESCRIPTION:
Cross Section 2483.2-Interpolated
END DESCRIPTION:
XS GIS Cut Line= 5
      3167638.66     13917761.42      3167310.64      13917118.4
      3167232.85     13917037.67      3167190.71     13916999.19
      3167094.76     13916911.57
#Sta/Elev= 30
  4152.4    67.4  4322.4    65.9  4362.4      63  4412.4    65.5  4442.4    66.3
  4522.4    66.6  4542.4    65.4  4562.4    65.3  4582.4    63.4  4612.4    58.1
  4642.4    57.2  4662.4    58.6  4682.4    61.6  4733.1   64.79  4812.4    65.5
  4832.4    64.9  4862.4    65.1  4884.3    65.8  4904.3    64.8  4961.2   64.41
  4991.6   55.88  4996.3   52.05  4999.8   51.24  5003.2   51.38  5007.4   54.73
  5031.8   63.17  5043.4    63.9  5053.4    65.8  5093.4    67.4  5173.4    68.1
#Mann= 5 , 1 , 0
  4152.4      .2       0  4152.4      .1       0  4733.1     .14       0
  4961.2     .04       0  5031.8     .14       0
#XS Ineff= 2 , 0
       0  4884.3    65.8               0
Permanent Ineff=
       F       F
Bank Sta=4961.2,5031.8
XS Rating Curve= 0
Exp/Cntr=.3,.1

Type RM Length L Ch R = 1 ,2081.6  ,551.1,544.4,535.8
BEGIN DESCRIPTION:
Cross Section 2081.6
END DESCRIPTION:
XS GIS Cut Line= 4
      3167870.06     13917114.73       3167368.2     13916690.14
      3167335.08     13916659.22      3167202.63      13916623.9
#Sta/Elev= 30
  4257.3    65.4  4427.3      65  4437.3    64.8  4597.3    64.3  4607.3    64.7
  4637.3    64.2  4647.3    64.2  4667.3    64.7  4757.3    64.7  4767.3    64.4
  4787.3    64.3  4797.3    64.5  4887.3    64.2  4907.3    65.7  4914.7    65.9
  4924.5   65.01  4947.3   63.95  4961.2   63.91  4991.6   55.38  4996.3   51.55
  4997.7    50.8  4999.8   50.74  5003.2   50.88  5003.7   51.62  5007.4   54.23
  5031.8   62.67  5054.8   62.34    5060    64.7    5070    64.8  5097.1      66
#Mann= 4 , 1 , 0
  4257.3      .2       0  4257.3     .14       0  4961.2     .04       0
  5031.8     .14       0
#XS Ineff= 2 , 0
       0  4914.7    65.9               0
Permanent Ineff=
       F       F
Bank Sta=4961.2,5031.8
XS Rating Curve= 0
Exp/Cntr=.3,.1

Type RM Length L Ch R = 1 ,1537.2  ,597.8,595.4,593.9
BEGIN DESCRIPTION:
Cross Section 1537.2-Interpolated
END DESCRIPTION:
XS GIS Cut Line= 3
      3167639.44     13916126.92      3167325.01     13916105.23
      3167234.96     13916103.68
#Sta/Elev= 19
  4681.1      65  4751.1    64.6  4761.1    64.2  4781.1    64.6  4871.1    64.4
  4931.1    64.7  4966.2   63.58  4990.1    53.4  4998.2   51.39  4998.9   51.17
  5000.8   50.63  5001.8   51.28  5009.3   54.38  5033.4   62.11  5046.3    62.7
  5056.3    63.7  5066.3    64.4  5076.3    66.9  5086.3    67.4
#Mann= 4 , 1 , 0
  4681.1      .2       0  4681.1     .14       0  4966.2     .04       0
  5033.4     .14       0
Bank Sta=4966.2,5033.4
XS Rating Curve= 0
Exp/Cntr=.3,.1

Type RM Length L Ch R = 1 ,941.8   ,562.1,564.9,567.5
BEGIN DESCRIPTION:
Cross Section 941.8
END DESCRIPTION:
XS GIS Cut Line= 3
       3167649.3      13915505.8      3167181.59     13915513.29
      3167033.56     13915498.57
#Sta/Elev= 23
    4699    64.1    4749    63.9    4759    63.5    4779    64.3    4789    63.9
    4819    63.2 4936.06   66.43 4959.37   63.49 4970.59   63.45 4991.39   53.27
 4998.43   51.26 4999.04   51.04  5000.7    50.5 5001.57   51.15 5008.09   54.25
 5029.06   61.98 5046.89   62.63    5059    63.3    5069    63.8  5166.8    63.7
  5276.8      63  5286.8    63.3  5315.5    64.3
#Mann= 5 , 1 , 0
    4699      .2       0    4699     .14       0 4970.59     .04       0
 5029.06     .14       0  5315.5      .2       0
#XS Ineff= 2 , 0
       0 4936.06   66.43               0
Permanent Ineff=
       F       F
Bank Sta=4970.59,5029.06
XS Rating Curve= 0
Exp/Cntr=.3,.1

Type RM Length L Ch R = 1 ,376.9   ,0,0,0
BEGIN DESCRIPTION:
Cross Section 376.9
END DESCRIPTION:
XS GIS Cut Line= 4
      3167672.64     13914953.28      3167394.78     13914945.96
      3167321.66     13914945.96      3167058.43     13914942.31
#Sta/Elev= 29
  4687.5   62.96  4699.5   62.79  4789.5   62.94  4819.5   62.62  4849.5   63.01
  4891.5   62.78  4909.5   62.17  4939.5   62.29  4965.5   61.48 4970.59   60.86
 4991.39   50.68 4998.43   48.67  5000.7   47.91 5001.57   48.56 5008.09   51.66
 5029.06   59.39  5038.6   60.52  5044.6   62.22  5074.6   62.89  5098.6   62.51
  5104.6   62.26  5110.6   61.69  5128.6   60.71  5134.6   60.64  5140.6   60.92
  5146.6   60.96  5176.6   61.92  5284.6   61.78  5301.8   61.59
#Mann= 5 , 1 , 0
  4687.5      .2       0  4687.5     .14       0 4970.59     .04       0
 5029.06     .14       0  5301.8      .2       0
Bank Sta=4970.59,5029.06
XS Rating Curve= 0
Exp/Cntr=.3,.1

Chan Stop Cuts=-1